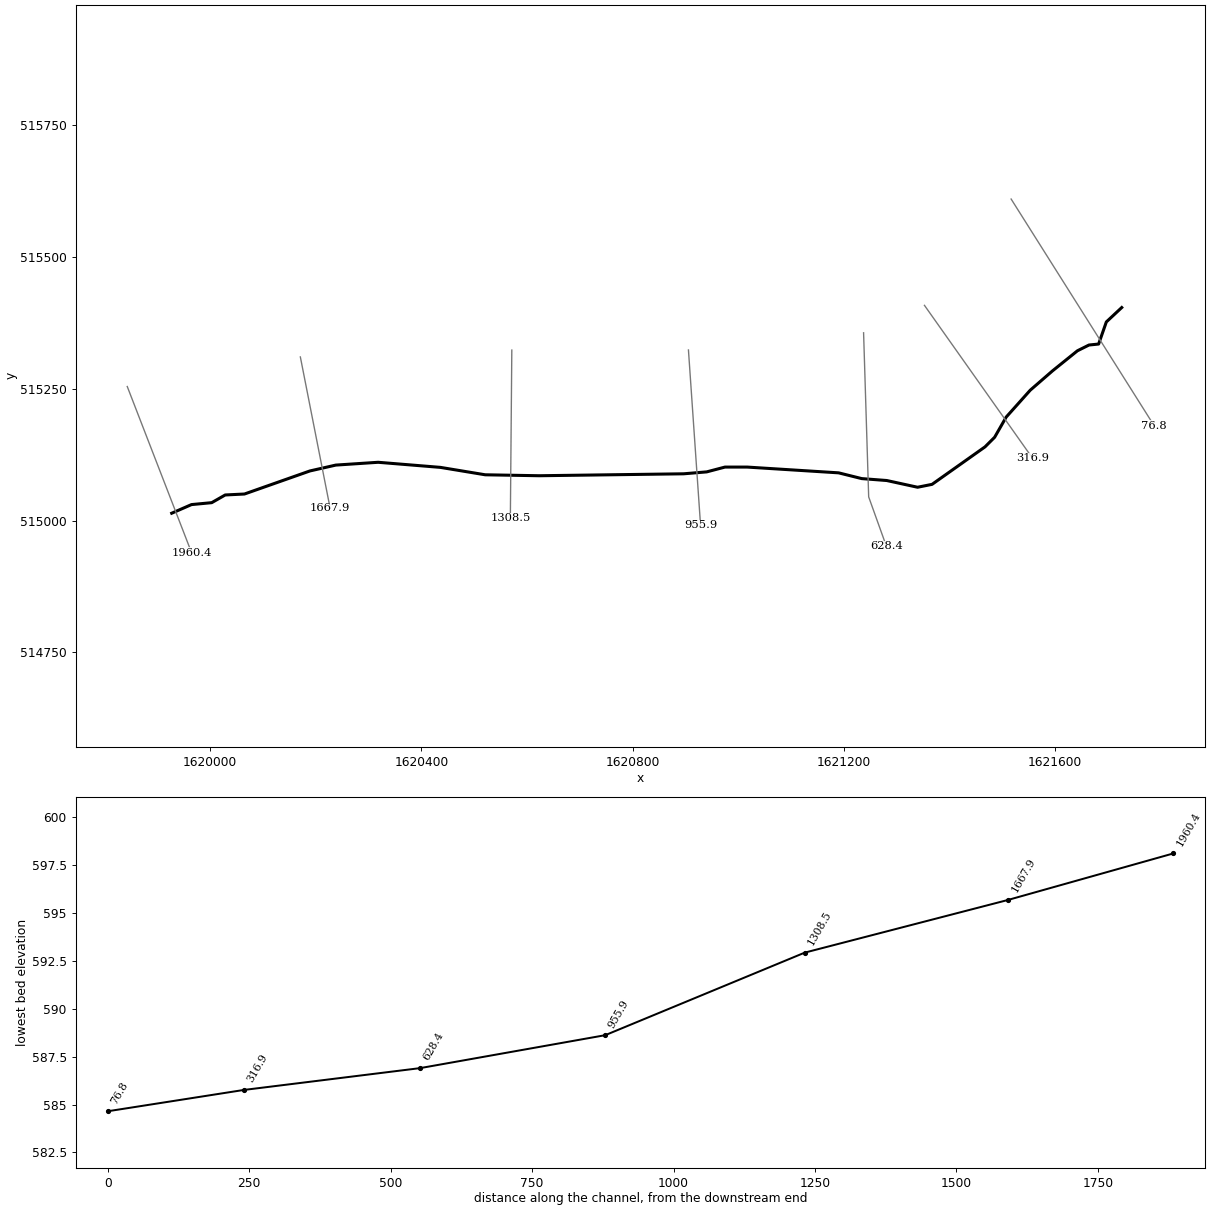
--- LFudgesCr.prj (project) ---

Proj Title=LFudgesCr
Current Plan=p01
Geom File=g01
Flow File=f01
Plan File=p01
DSS Export Rating Curves=0
DSS Export Rating Curve Sorted=0
DSS Export Volume Flow Curves=0
DXF OffsetX=0
DXF OffsetY=0
DXF ScaleX=0
DXF ScaleY=0

--- LFudgesCr.p01 (plan) ---

Plan Title=Floodplain
Program Version=4.00
Geom File=g01
Flow File=f01
K Sum by GR=0
Std Step Tol=0.01
Critical Tol=0.01
Num of Std Step Trials=20
Max Error Tol=0.3
Flow Tol Ratio=0.001
Split Flow NTrial=30
Split Flow Tol=0.02
Split Flow Ratio=0.02
Log Output Level=0
Friction Slope Method=1
Unsteady Friction Slope Method=2
Unsteady Bridges Friction Slope Method=1
Global Log Level=0
CheckData=False
Run HTab=0
Run UNet=0
Run PostProcess=0
UNET Theta=0
UNET Theta Warmup=0
UNET ZTol=0
UNET ZSATol=0
UNET MxIter=0
UNET MaxInSteps=0
UNET DtIC=0
UNET DtMin=0
UNET MaxCRTS=0
UNET WFStab=0
UNET SFStab=0
UNET WFX=0
UNET SFX=0
UNET DSS MLevel=0
UNET DZMax Abort=0
UNET Convert EG Bridges=0
UNET Use Existing IB Tables=0
UNET Froude Limit=0
UNET Froude Power=0
Write IC File=0
Echo Input=False
Echo Output=False
Write Detailed=0

--- LFudgesCr.f01 (steady flow) ---

Flow Title=NFF Regression Equation
Program Version=4.10
Number of Profiles= 1
Profile Names=P100yr
River Rch & RM=LFudgesCr,Main            ,1960.4
     898
River Rch & RM=LFudgesCr,Main            ,1667.9
     899
River Rch & RM=LFudgesCr,Main            ,955.9
     908
River Rch & RM=LFudgesCr,Main            ,316.9
     914
Boundary for River Rch & Prof#=LFudgesCr,Main            , 1
Up Type= 0
Dn Type= 3
Dn Slope=0.00477
DSS Import GetInterval= 0
DSS Import GetPeak= 0
DSS Import FillOption= 0

--- LFudgesCr.g01 (geometry) ---

Geom Title=USGS 10m DEM
Program Version=4.10

River Reach=LFudgesCr       ,Main
Reach XY= 30
     1619927.213      515014.105     1619964.677      515030.487
     1620002.972      515034.132     1620028.501      515048.736
     1620064.958      515050.543     1620188.929      515094.326
     1620237.864      515105.428     1620318.054       515110.75
     1620435.925      515101.091     1620520.785       515087.03
     1620622.871      515085.232     1620896.382      515088.893
     1620940.124      515092.538     1620974.775      515101.663
     1621016.713      515101.666      1621189.91      515090.717
     1621233.685      515079.793      1621281.07      515076.153
     1621339.415      515063.392     1621366.783      515068.874
      1621467.06       515139.99     1621485.271      515158.204
     1621507.156        515196.5     1621552.732      515247.563
     1621594.667      515284.023     1621642.082      515322.321
     1621663.968       515333.25      1621682.18      515335.088
      1621696.78      515377.027     1621725.951      515404.363

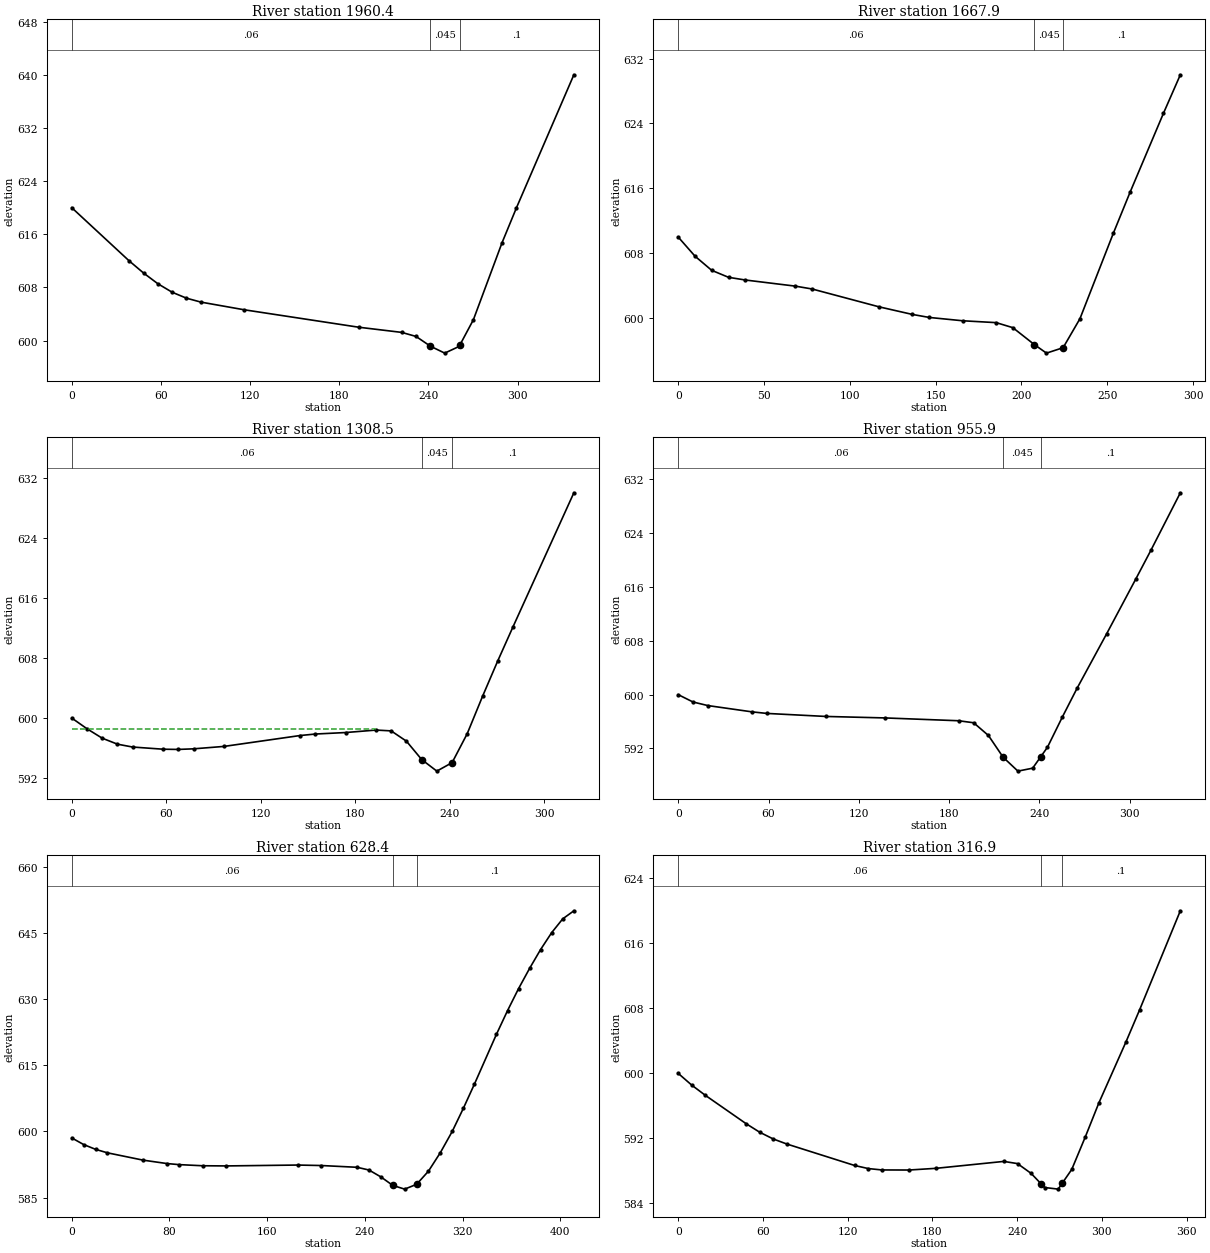
Type RM Length L Ch R = 1 ,1960.4  ,296.5,292.5,288.5
XS GIS Cut Line= 2
     1619843.057      515254.482     1619964.834      514939.263
#Sta/Elev= 19
       0     620    38.6     612    48.3  610.17    57.9  608.56    67.6  607.27
    77.2  606.38    86.9  605.79   115.9  604.64   193.1  602.01   222.1  601.23
   231.7  600.62   241.4  599.15     251  598.11   260.7  599.12   261.3  599.37
   270.3  603.14   289.6  614.74   299.3     620   337.9     640
#Mann= 3 , 0 , 0
       0     .06       0   241.4    .045       0   261.3      .1       0
Bank Sta=241.4,261.3
XS Rating Curve= 0 ,0
Exp/Cntr=0.3,0.1

Type RM Length L Ch R = 1 ,1667.9  ,363.8,359.3,354.7
XS GIS Cut Line= 2
     1620170.775      515310.621     1620227.173      515023.527
#Sta/Elev= 21
       0  609.99     9.8  607.63    19.5  605.89    29.3  605.03      39   604.7
    68.3  603.94      78  603.59     117  601.39   136.5  600.45   146.3  600.08
   165.8  599.67   185.3  599.44     195  598.82   207.5  596.74   214.6  595.68
   224.3  596.35   234.1  599.92   253.6  610.48   263.3  615.51   282.8  625.27
   292.6     630
#Mann= 3 , 0 , 0
       0     .06       0   207.5    .045       0   224.3      .1       0
Bank Sta=207.5,224.3
XS Rating Curve= 0 ,0
Exp/Cntr=0.3,0.1

Type RM Length L Ch R = 1 ,1308.5  ,350.9,352.7,354.4
XS GIS Cut Line= 2
      1620571.15      515323.632     1620568.388      515004.888
#Sta/Elev= 23
       0     600     9.7  598.57    19.3  597.32      29  596.52    38.6  596.14
      58  595.85    67.6  595.82    77.3   595.9    96.6  596.22   144.9  597.67
   154.6  597.87   173.9  598.07   193.2   598.4   202.8  598.29   212.5  596.92
   222.2  594.47   231.8  592.93   241.5  594.06   251.1  597.92   260.8  602.88
   270.5  607.62   280.1  612.12   318.8     630
#Mann= 3 , 0 , 0
       0     .06       0   222.2    .045       0   241.5      .1       0
#XS Ineff= 2 , 0
          192.75  598.55
Permanent Ineff=
       F       F
Bank Sta=222.2,241.5
XS Rating Curve= 0 ,0
Exp/Cntr=0.3,0.1

Type RM Length L Ch R = 1 ,955.9   ,328.2,327.4,326.4
XS GIS Cut Line= 2
     1620905.571      515323.855     1620928.526      514991.011
#Sta/Elev= 21
       0  599.99     9.8   598.9    19.6  598.37    49.1  597.43    58.9   597.2
    98.1  596.75   137.4  596.53   186.4  596.11   196.3  595.81   206.1  593.92
   215.9  590.68   225.7  588.62   235.5  589.06   240.9  590.77   245.3  592.16
   255.1  596.61     265  600.94   284.6  609.02   304.2  617.26     314  621.43
   333.6     630
#Mann= 3 , 0 , 0
       0     .06       0   215.9    .045       0   240.9      .1       0
Bank Sta=215.9,240.9
XS Rating Curve= 0 ,0
Exp/Cntr=0.3,0.1

Type RM Length L Ch R = 1 ,628.4   ,298.6,311.6,324.3
XS GIS Cut Line= 3
     1621237.177      515356.441     1621246.814      515045.115
      1621280.32      514951.456
#Sta/Elev= 30
       0  598.51     9.7  597.01    19.5  595.92    29.2  595.13    58.4  593.47
    77.9   592.7    87.6  592.46   107.1   592.2   126.5  592.16   184.9  592.36
   204.4  592.25   233.6  591.85   243.3  591.23   253.1  589.66   262.8  587.74
   272.5   586.9   282.3  587.99     292  590.98   301.7  595.16   311.5  600.01
   320.5  605.19   329.6   610.7   347.6  621.98   356.7  627.36   365.7  632.34
   374.8  636.96   383.8  641.23   392.9  645.07   401.9  648.18     411     650
#Mann= 3 , 0 , 0
       0     .06       0   262.8    .045       0   282.3      .1       0
Bank Sta=262.8,282.3
XS Rating Curve= 0 ,0
Exp/Cntr=0.3,0.1

Type RM Length L Ch R = 1 ,316.9   ,241.1,240.1,239.1
XS GIS Cut Line= 2
     1621352.429      515408.493     1621557.425      515117.943
#Sta/Elev= 25
       0     600     9.6  598.55    19.2   597.3      48  593.82    57.7  592.76
    67.3  591.93    76.9  591.31   124.9  588.67   134.6  588.29   144.2  588.12
   163.4  588.11   182.6  588.32   230.6  589.17   240.3   588.9   249.9   587.7
   256.9  586.43   259.5  585.96   269.1  585.76   271.9  586.47   278.7  588.18
   288.3  592.18   297.9  596.36   317.2  603.91   326.8  607.83   355.6     620
#Mann= 3 , 0 , 0
       0     .06       0   256.9    .045       0   271.9      .1       0
Bank Sta=256.9,271.9
XS Rating Curve= 0 ,0
Exp/Cntr=0.3,0.1

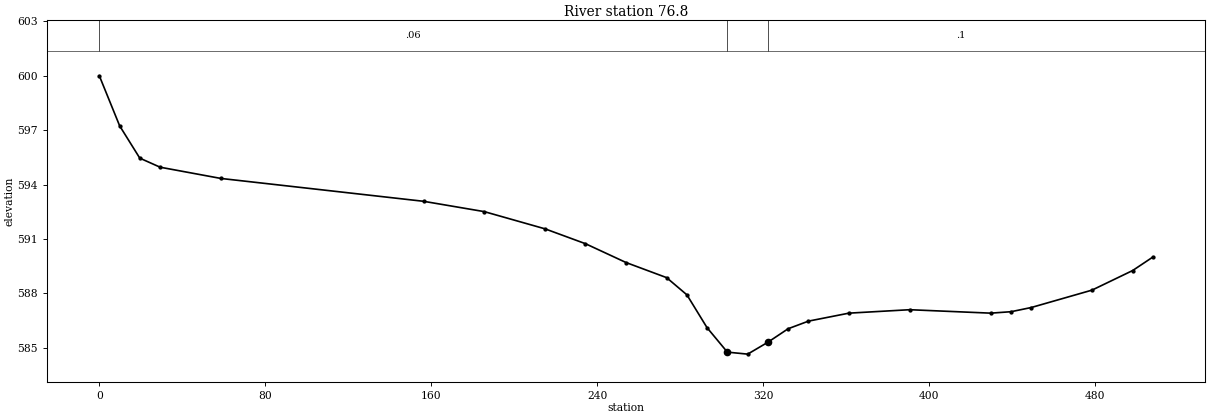
Type RM Length L Ch R = 1 ,76.8    ,69.3,76.8,83.1
XS GIS Cut Line= 2
      1621516.54      515610.207     1621787.172      515180.367
#Sta/Elev= 26
       0     600     9.8  597.24    19.5  595.46    29.3  594.96    58.6  594.34
   156.3  593.08   185.6  592.51   214.9  591.56   234.4  590.74     254   589.7
   273.5  588.87   283.3  587.92     293  586.11   302.8  584.76   312.6  584.65
   322.4  585.31   332.1  586.05   341.9  586.47   361.4  586.91   390.7   587.1
   429.8  586.91   439.6  586.99   449.3  587.22   478.6  588.18   498.2  589.26
   507.9     590
#Mann= 3 , 0 , 0
       0     .06       0   302.8    .045       0   322.4      .1       0
Bank Sta=302.8,322.4
XS Rating Curve= 0 ,0
Exp/Cntr=0.3,0.1

Chan Stop Cuts=-1
Use User Specified Reach Order=0
Composite Channel Slope=5